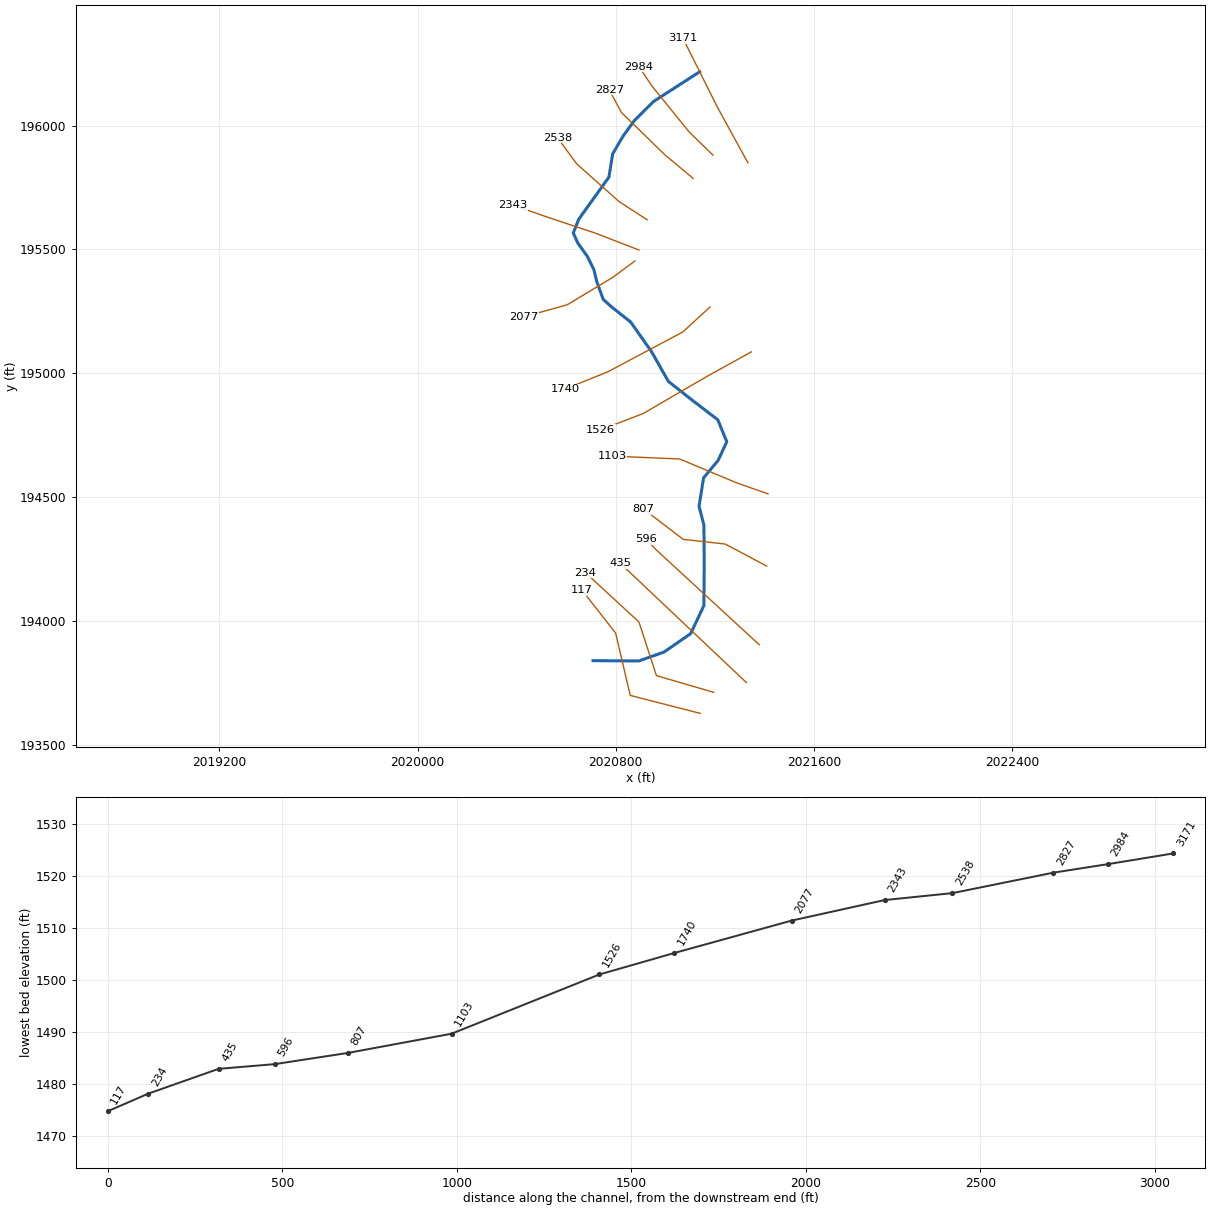
--- BRDSHWCK1_A.prj (project) ---

Proj Title=BRDSHWCK1_A
Current Plan=p01
Default Exp/Contr=0,0
English Units
Geom File=g01
Flow File=f01
Plan File=p01
BEGIN DESCRIPTION:
Stream Name: Bradshaw Creek
Flood Zone: Approximate
Summers County, West Virginia
HEC-RAS Version: 5.0.7
Hydrology Method:
Regression.
Model Notes:
END DESCRIPTION:
DSS Export Rating Curves= 0
DSS Export Rating Curve Sorted= 0
DSS Export Volume Flow Curves= 0
DXF OffsetX= 0
DXF OffsetY= 0
DXF ScaleX= 0
DXF ScaleY= 0

--- BRDSHWCK1_A.p01 (plan) ---

Plan Title=Floodplain
Program Version=5.07
Short Identifier=Floodplain
Geom File=g01
Flow File=f01
Subcritical Flow
K Sum by GR= 0
Std Step Tol= 0.01
Critical Tol= 0.01
Num of Std Step Trials= 20
Max Error Tol= 0.3
Flow Tol Ratio= 0.001
Split Flow NTrial= 30
Split Flow Tol= 0.02
Split Flow Ratio= 0.02
Log Output Level= 0
Friction Slope Method= 1
Unsteady Friction Slope Method= 2
Unsteady Bridges Friction Slope Method= 1
Parabolic Critical Depth
Global Vel Dist= 0 , 0 , 0
Global Log Level= 0
CheckData=True
Encroach Param=-1 ,0,0, 0
Mapping Interval=1HOUR
Computation Time Step Use Courant=        0
Computation Time Step Use Time Series=    0
Computation Time Step Count To Double=0
Computation Time Step Max Doubling=0
Computation Time Step Max Halving=0
Computation Time Step Residence Courant=0
Run HTab= 0
Run UNet= 0
Run Sediment= 0
Run PostProcess= 0
Run WQNet= 0
Run RASMapper= 0
UNET Theta= 0
UNET Theta Warmup= 0
UNET ZTol= 0
UNET ZSATol= 0
UNET MxIter= 0
UNET Max Iter WO Improvement= 0
UNET MaxInSteps= 0
UNET DtIC= 0
UNET DtMin= 0
UNET MaxCRTS= 0
UNET WFStab= 0
UNET SFStab= 0
UNET WFX= 1
UNET SFX= 1
UNET 1D Methodology=Finite Difference
UNET DSS MLevel= 1
UNET Pardiso=0
UNET DZMax Abort= 0
UNET Use Existing IB Tables= 0
UNET Froude Reduction=False
UNET Froude Limit= 0
UNET Froude Power= 0
UNET D1 Cores= 0
UNET D2 Coriolis=0
UNET D2 Cores= 0
UNET D2 Theta= 1
UNET D2 Theta Warmup= 1
UNET D2 Z Tol= 0.01
UNET D2 Volume Tol= 0.01
UNET D2 Max Iterations= 20
UNET D2 Equation= 0
UNET D2 RampUpFraction=0.1
UNET D2 TimeSlices= 1
UNET D2 BCVolumeCheck=0
UNET D1D2 MaxIter= 0
UNET D1D2 ZTol=0.01
UNET D1D2 QTol=0.1
UNET D1D2 MinQTol=1
Write IC File= 0
Write IC File at Fixed DateTime=0
Write IC File at Sim End=0
Echo Input=False
Echo Parameters=False
Echo Output=False
Write Detailed= 0
HDF Write Warmup=0
HDF Write Time Slices=0
HDF Flush=0
HDF Face Node Velocities=0
HDF Compression= 1
HDF Chunk Size= 1
HDF Spatial Parts= 1
HDF Use Max Rows=0
HDF Fixed Rows= 1
Calibration Method= 0
Calibration Iterations= 20
Calibration Max Change=0.05
Calibration Tolerance=0.2
Calibration Maximum=1.5
Calibration Minimum=0.5
Calibration Optimization Method= 1
WQ AD Non Conservative
WQ ULTIMATE=-1
WQ Max Comp Step=1HOUR
WQ Output Interval=15MIN
WQ Output Selected Increments= 0
WQ Output face flow=0
WQ Output face velocity=0
WQ Output face area=0
WQ Output face dispersion=0
WQ Output cell volume=0
WQ Output cell surface area=0
WQ Output cell continuity=0
WQ Output cumulative cell continuity=0
WQ Output face conc=0
WQ Output face dconc_dx=0
WQ Output face courant=0
WQ Output face peclet=0
WQ Output face adv mass=0
WQ Output face disp mass=0
WQ Output cell mass=0
WQ Output cell source sink temp=0
WQ Output nsm pathways=0
WQ Output nsm derived pathways=0
WQ Output MaxMinRange=-1
WQ Daily Max Min Mean=-1
WQ Daily Range=0
WQ Daily Time=0
WQ Create Restart=0
WQ Fixed Restart=0
WQ System Summary=0
WQ Write To DSS=0
WQ Use Fixed Temperature=0
Sorting and Armoring Iterations= 10
XS Update Threshold= 0.02
Bed Roughness Predictor= 0
Hydraulics Update Threshold= 0.02
Energy Slope Method= 1
Volume Change Method= 1
Sediment Retention Method= 0
XS Weighting Method= 0
Number of US Weighted Cross Sections= 1
Number of DS Weighted Cross Sections= 1
Upstream XS Weight=0
Main XS Weight=1
Downstream XS Weight=0
Number of DS XS's Weighted with US Boundary= 1
Upstream Boundary Weight= 1
Weight of XSs Associated with US Boundary= 0
Number of US XS's Weighted with DS Boundary= 1
Downstream Boundary Weight= 0.5
Weight of XSs Associated with DS Boundary= 0.5
Percentile Method= 0
Sediment Output Level= 3
Mass or Volume Output= 0
Output Increment Type= 1
Profile and TS Output Increment= 1
XS Output Flag= 0
XS Output Increment= 10
Write Gradation File= 0
Read Gradation Hotstart= 0
Write HDF5 File= 1
Write Binary Output= 1
Write DSS Sediment File= 0
SV Curve= 0
Specific Gage Flag= 0

--- BRDSHWCK1_A.f01 (steady flow) ---

Flow Title=Flows
Program Version=5.07
Number of Profiles= 6
Profile Names=01pct,10pct,04pct,02pct,0_2pct,01plus
River Rch & RM=BRDSHWCK1_A,Main            ,3171
    2234    1245    1613    1914    3042    3304
Boundary for River Rch & Prof#=BRDSHWCK1_A,Main            , 1
Up Type= 0
Dn Type= 3
Dn Slope=0.010565
Boundary for River Rch & Prof#=BRDSHWCK1_A,Main            , 2
Up Type= 0
Dn Type= 3
Dn Slope=0.010565
Boundary for River Rch & Prof#=BRDSHWCK1_A,Main            , 3
Up Type= 0
Dn Type= 3
Dn Slope=0.010565
Boundary for River Rch & Prof#=BRDSHWCK1_A,Main            , 4
Up Type= 0
Dn Type= 3
Dn Slope=0.010565
Boundary for River Rch & Prof#=BRDSHWCK1_A,Main            , 5
Up Type= 0
Dn Type= 3
Dn Slope=0.010565
Boundary for River Rch & Prof#=BRDSHWCK1_A,Main            , 6
Up Type= 0
Dn Type= 3
Dn Slope=0.010565
DSS Import GetInterval= 0
DSS Import GetPeak= 0
DSS Import FillOption= 0

--- BRDSHWCK1_A.g01 (geometry) ---

Geom Title=Geometry
Program Version=5.07

River Reach=BRDSHWCK1_A     ,Main
Reach XY= 30
2021138.75100598196217.346601567     2020952.571196097.572000033
     2020875.314196021.008999978     2020828.873195956.947000035
2020787.20600002195885.3319999722020772.30900001195792.064000039
     2020650.488195622.3110000432020628.35200001195566.322000024
2020646.58200002195525.9570000172020685.64400003195471.270000021
     2020711.686195417.8839999982020723.40400003195369.707000063
2020749.44600001195298.0920000392020784.60200003 195266.84200005
2020860.12299999 195206.946999992020943.45600001195088.456999983
2021012.46700002194967.363000017     2021098.852194899.033999989
     2021211.686194812.416000042     2021248.144194723.874000017
2021212.98800002194648.352999996     2021154.394194578.040000034
2021136.16500001194463.457000024     2021155.696 194386.63400001
2021156.99800001194240.801000005      2021155.71194062.589999996
     2021102.311193949.133999983     2020994.686193874.727999979
2020893.10900001193838.8910000152020708.22700002193840.006000027

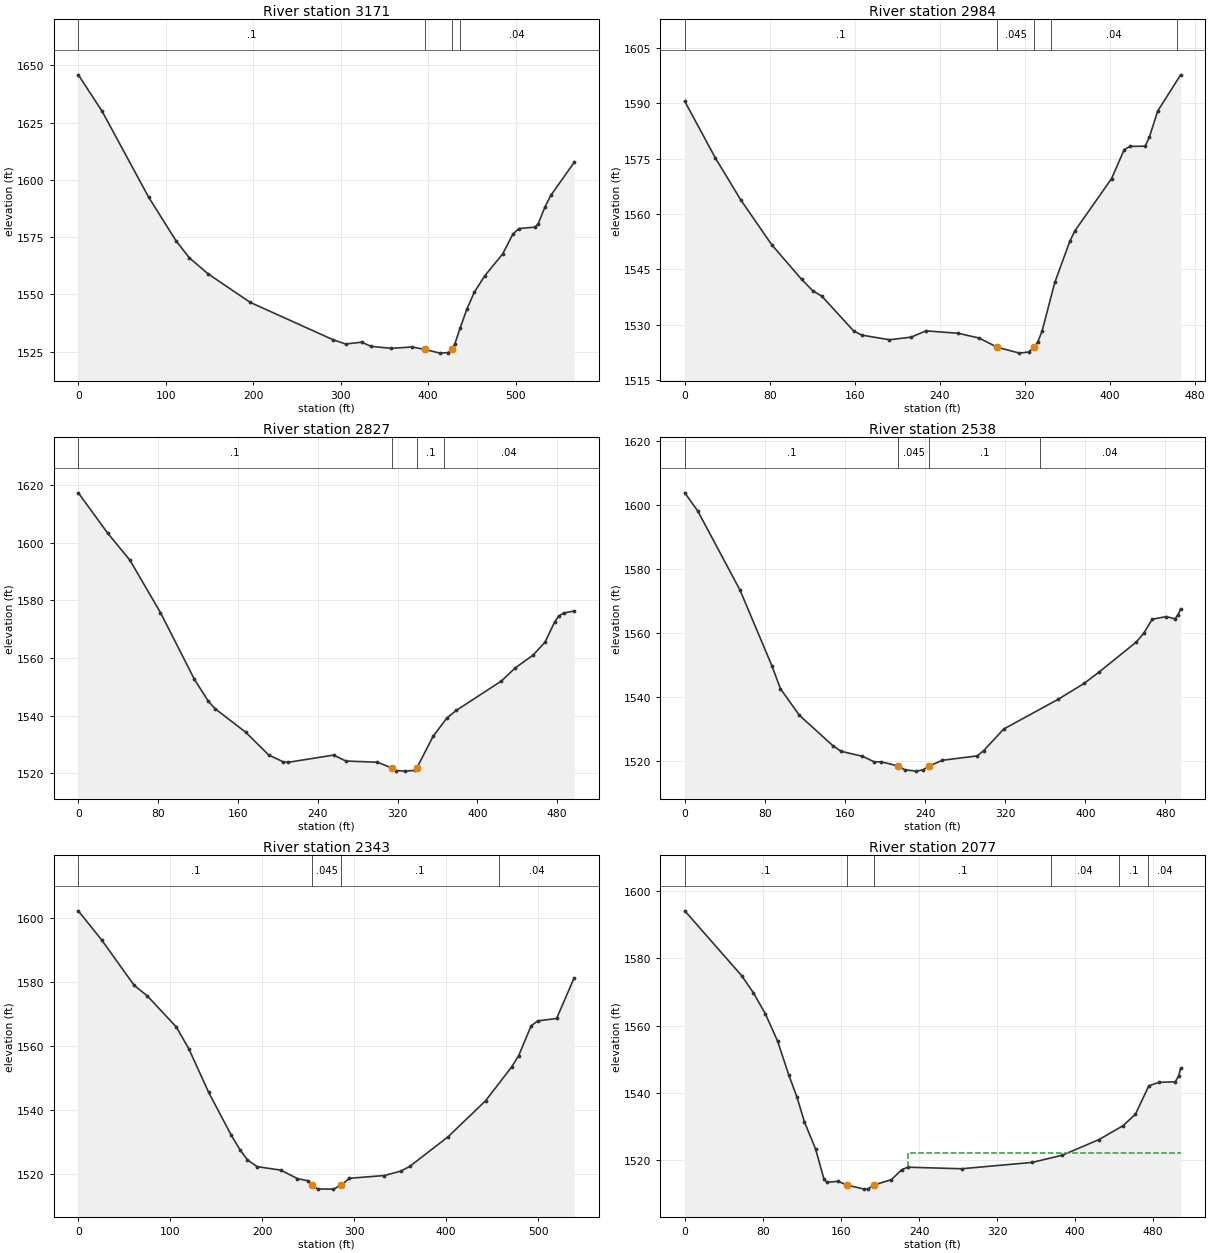
Type RM Length L Ch R = 1 ,3171    ,171.9,187.1,191.7
XS GIS Cut Line= 3
     2021333.353      195849.943     2021209.982      196074.822
     2021071.197      196352.352
#Sta/Elev= 30
       0 1645.85    27.2 1629.93    80.3 1592.51   111.6 1573.47   126.8 1566.04
     148  1559.1   196.3 1546.58   290.8 1530.31   305.5 1528.39   323.8 1529.16
   334.8 1527.35   357.4  1526.5   381.5 1527.07   396.1 1526.03   413.3  1524.4
   422.9 1524.64   427.2 1526.08   430.2 1528.22   436.5 1535.39   444.3 1543.73
   452.7 1551.01   464.6 1558.14   485.2 1567.76   496.7 1576.32   503.6 1578.76
   521.9 1579.38   525.6 1580.74   533.4 1588.19   540.2 1593.28   566.8 1607.64
#Mann= 4 ,-1 , 0
       0      .1       0   396.1    .045       0   427.2      .1       0
   436.5     .04       0
Bank Sta=396.1,427.2
XS Rating Curve= 0 ,0
Exp/Cntr=0.3,0.1

Type RM Length L Ch R = 1 ,2984    ,150.4,157,159.1
XS GIS Cut Line= 4
2021192.01646618195881.0623847732021095.64448868195975.083826236
2020945.21018234196160.7761731272020893.49838953196238.343862334
#Sta/Elev= 30
       0 1590.47    28.8 1575.15    52.6 1563.85    81.8 1551.69     110  1542.3
   120.4 1539.25   129.2  1537.7   158.9 1528.36   166.5 1527.22   192.7 1525.96
   213.1 1526.67   227.1 1528.37   257.5 1527.71   277.1 1526.42  294.111523.946
   315.1 1522.34   323.6 1522.64  328.911523.947   332.2 1525.28   336.3 1528.25
   348.4 1541.52   362.4 1552.55   367.1 1555.37   401.8 1569.58   413.6 1577.36
     419 1578.28   433.4 1578.34   437.3 1580.74   445.2 1587.84   466.8 1597.65
#Mann= 5 ,-1 , 0
       0      .1       0  294.11    .045       0  328.91      .1       0
  344.64     .04       0  463.62      .1       0
Bank Sta=294.11,328.91
XS Rating Curve= 0 ,0
Exp/Cntr(USF)=0,0
Exp/Cntr=0.3,0.1

Type RM Length L Ch R = 1 ,2827    ,273.1,289.2,276
XS GIS Cut Line= 4
2021112.09824093195787.0409433092020999.27251118195881.062384773
2020822.98230843196052.6515154442020773.62105166 196144.32242087
#Sta/Elev= 30
       0 1617.34    29.5 1603.31    51.6 1594.01    82.3 1575.77   116.4 1552.54
   130.4 1544.92   137.4 1542.29   167.6 1534.25   190.8 1526.32   205.2 1523.93
   209.9 1523.73   255.8 1526.26   268.3 1524.19   299.8 1523.79  314.161521.791
   318.4 1520.88   327.5 1520.69     337 1520.94  339.32 1521.79   355.5 1532.72
   369.4 1539.14   378.7 1541.75   424.1 1551.99     438 1556.56   455.6 1560.91
   467.8 1565.49   477.4 1572.45   481.4  1574.5   486.4  1575.6     497 1576.29
#Mann= 4 ,-1 , 0
       0      .1       0  314.16    .045       0  339.32      .1       0
  366.87     .04       0
Bank Sta=314.16,339.32
XS Rating Curve= 0 ,0
Exp/Cntr(USF)=0,0
Exp/Cntr=0.3,0.1

Type RM Length L Ch R = 1 ,2538    ,177.5,194.4,215.1
XS GIS Cut Line= 4
2020926.40589404195620.1528847122020813.58016429195693.019501846
2020641.99103362195845.8043442242020564.42334441 195951.57846587
#Sta/Elev= 30
       0 1603.74      13 1598.03    55.2  1573.3    87.2 1549.52    95.5 1542.51
   114.5 1534.19   147.7 1524.76     156 1522.95   177.4 1521.39   189.3 1519.64
   196.2 1519.66  213.321518.341   219.5 1517.18   231.1 1516.75   238.1 1517.16
  244.211518.341     257 1520.13   292.1 1521.52   298.5 1523.15   318.5 1529.91
   373.1 1539.24   398.8 1544.17   413.5 1547.65   450.8 1557.07   458.3  1559.8
   466.8 1564.23   480.9 1565.05   489.6 1564.35   492.6 1565.65   495.2 1567.47
#Mann= 4 ,-1 , 0
       0      .1       0  213.32    .045       0  244.21      .1       0
  354.31     .04       0
Bank Sta=213.32,244.21
XS Rating Curve= 0 ,0
Exp/Cntr(USF)=0,0
Exp/Cntr=0.3,0.1

Type RM Length L Ch R = 1 ,2343    ,233.4,266.7,297.1
XS GIS Cut Line= 4
2020893.49838953195497.9250108092020717.20818679 195566.09055587
2020519.76315971195631.9055648952020385.78260563195678.916285626
#Sta/Elev= 30
       0 1602.08    25.6 1592.92    60.8 1578.84    74.9 1575.62   106.5 1565.92
     120 1559.19   141.7 1545.55   166.3 1532.19   176.2 1527.47   183.9 1524.53
   194.4 1522.41     220 1521.33   238.2  1518.7   249.7    1518  254.431516.665
   260.1 1515.47   277.4 1515.41  285.811516.666   294.7 1518.78   332.7 1519.65
   350.6 1521.02   360.4  1522.5   401.9 1531.69   442.8 1542.93   471.1 1553.45
   478.8 1556.98   492.3 1566.27   499.4 1567.79     520 1568.55   539.1  1581.2
#Mann= 4 ,-1 , 0
       0      .1       0  254.43    .045       0  285.81      .1       0
  457.14     .04       0
Bank Sta=254.43,285.81
XS Rating Curve= 0 ,0
Exp/Cntr(USF)=0,0
Exp/Cntr=0.3,0.1

Type RM Length L Ch R = 1 ,2077    ,335.4,336.4,332.9
XS GIS Cut Line= 4
2020877.04463727195453.2648261142020787.72426788 195387.44981709
2020604.38245703 195276.974623372020428.09225429195227.613366602
#Sta/Elev= 30
       0 1594.07    58.2 1574.84    70.4 1569.71    82.6 1563.46      95 1555.46
   106.7 1545.23     115 1538.73   122.6 1531.42   134.1  1523.3   142.5 1514.53
   145.6 1513.46   157.1 1513.77  166.071512.659   183.9 1511.45   187.9 1511.55
  193.661512.659   211.8 1514.28   222.2  1517.2   228.5 1517.96   283.6  1517.5
   356.2 1519.39   386.9 1521.53   424.4 1526.15   449.1 1530.29   461.8 1533.67
   475.5 1542.11   485.7 1543.14   502.7 1543.32   506.1  1545.1   508.1 1547.31
#Mann= 6 ,-1 , 0
       0      .1       0  166.07    .045       0  193.66      .1       0
     375     .04       0     445      .1       0     475     .04       0
#XS Ineff= 2 , 0
                          228.65         1522.16
Permanent Ineff=
       F       F
Bank Sta=166.07,193.66
XS Rating Curve= 0 ,0
Exp/Cntr(USF)=0,0
Exp/Cntr=0.3,0.1

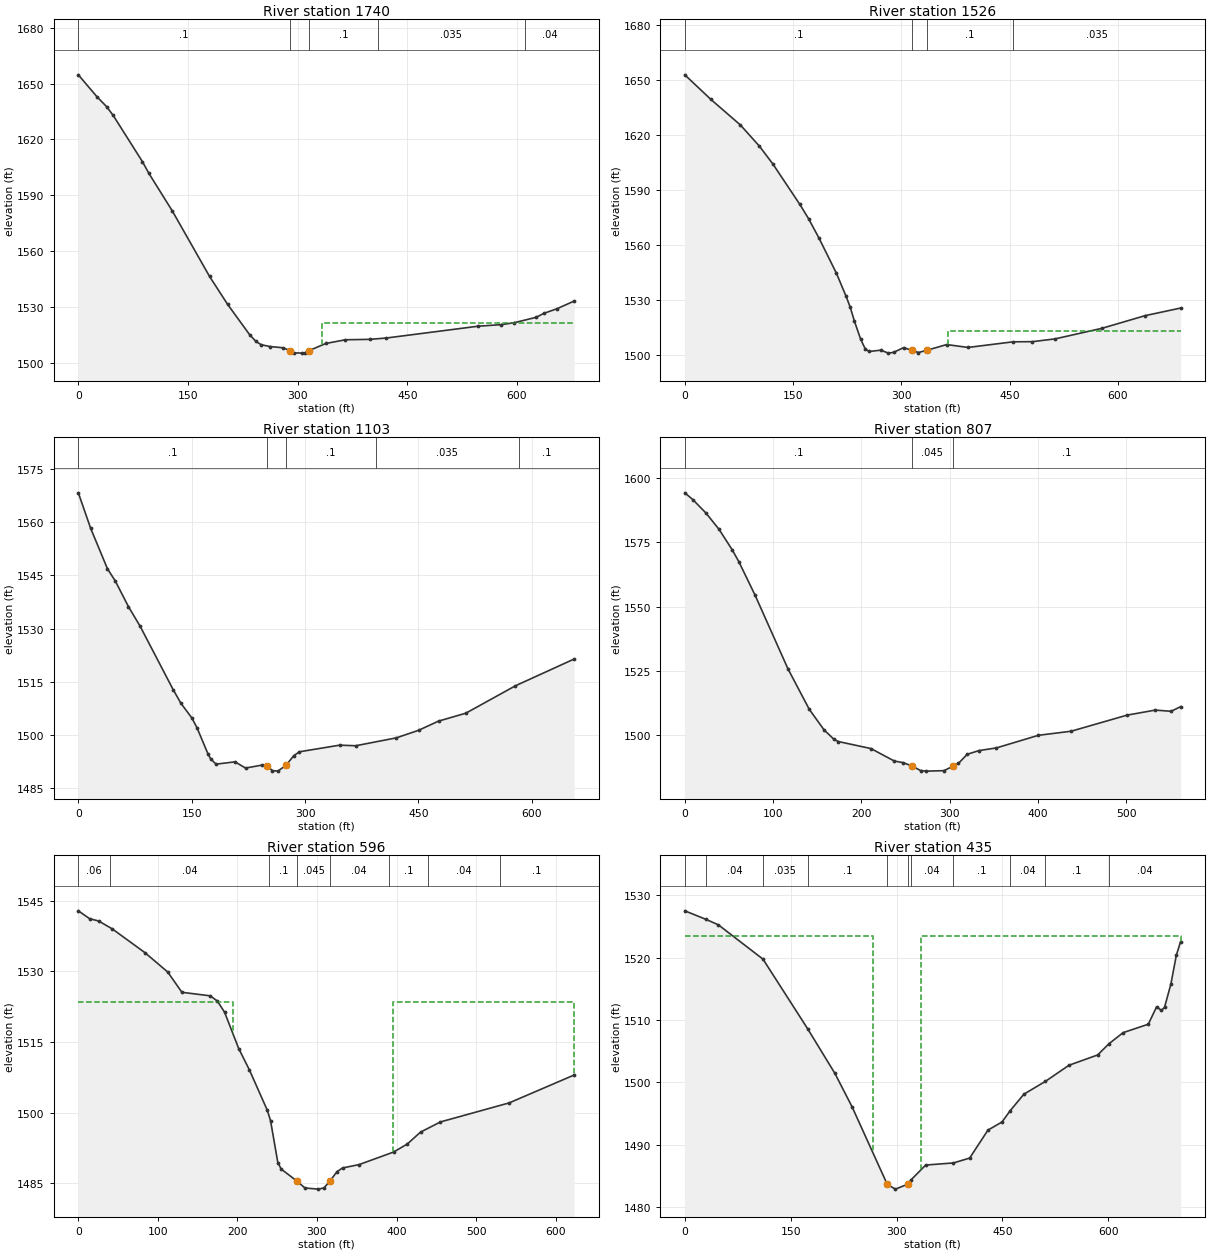
Type RM Length L Ch R = 1 ,1740    ,212.4,214.4,214.8
XS GIS Cut Line= 4
2021180.26378599195267.5724792242021069.78859227195166.499429651
2020768.91997959195006.6629791632020594.98031288194936.146898065
#Sta/Elev= 30
       0 1654.74    25.3 1643.05    38.7 1637.62    47.6 1632.97    87.6 1608.13
    96.5 1601.77   128.4 1581.69   179.5 1546.39   204.2 1531.38   234.2 1515.14
   242.7 1511.58   250.1  1509.7   262.5 1508.73   280.3 1508.06  289.631506.514
   294.9 1505.35   305.8  1505.2   309.6 1505.33  315.221506.514   338.5 1510.39
   365.3 1512.38   398.7  1512.6     421 1513.31   546.8 1519.67   578.4  1520.5
   595.9 1521.52   626.1 1524.44   636.7 1526.58   654.4 1529.02   678.1 1533.18
#Mann= 5 ,-1 , 0
       0      .1       0  289.63    .045       0  315.22      .1       0
  409.73    .035       0  610.42     .04       0
#XS Ineff= 2 , 0
                          332.95         1521.65
Permanent Ineff=
       F       F
Bank Sta=289.63,315.22
XS Rating Curve= 0 ,0
Exp/Cntr(USF)=0,0
Exp/Cntr=0.3,0.1

Type RM Length L Ch R = 1 ,1526    ,421.6,423.2,335.1
XS GIS Cut Line= 4
2021347.15184459195086.5812044072021168.51110581 194987.85869087
2020909.95214179194837.4243845292020738.36301112194771.609375504
#Sta/Elev= 30
       0 1652.99    36.2 1639.55    77.1 1625.58   103.3 1614.09   122.1 1604.28
   159.3 1582.31   171.4 1574.52   185.8 1563.97     210 1544.75   223.5 1532.08
   229.2 1526.15   234.9 1518.67   243.6 1508.73   250.1 1503.31   255.6 1501.97
   271.6 1502.69     282 1501.07   289.2 1501.48   303.2 1504.05   314.6  1502.6
   323.8 1501.41   335.6 1502.64   362.9 1505.75   392.4 1504.17     455 1507.25
   481.6 1507.33   512.9 1508.83   578.1 1514.63   637.8 1521.53     687 1525.68
#Mann= 4 ,-1 , 0
       0      .1       0   314.6    .045       0   335.6      .1       0
   454.1    .035       0
#XS Ineff= 2 , 0
                          365.04         1513.18
Permanent Ineff=
       F       F
Bank Sta=314.6,335.6
XS Rating Curve= 0 ,0
Exp/Cntr(USF)=0,0
Exp/Cntr=0.3,0.1

Type RM Length L Ch R = 1 ,1103    ,277.7,296.1,300
XS GIS Cut Line= 4
 2021414.4920098194513.4509552462021288.38844368194557.710596175
2021058.03591209194654.0825736752020785.37373185194665.835253858
#Sta/Elev= 30
       01568.384  16.3281558.333   38.551546.898  48.9811543.422  66.3661536.183
  81.8031530.636 125.4761512.728 135.9591508.792 150.1841504.728 157.2971501.821
 171.5231494.559 175.0791493.158 182.192 1491.63 207.4061492.289 221.3121490.528
  242.651491.351 250.0311491.121 256.8761489.801 263.989 1489.66 274.6581491.253
 285.1351494.023 292.6571495.132 345.7861497.004 367.124 1496.84 420.9091499.072
 450.4641501.219 476.7351503.807 512.8571506.048 578.5351513.801  656.261521.374
#Mann= 5 ,-1 , 0
       0      .1       0 250.031    .045       0 274.658      .1       0
  393.34    .035       0  583.34      .1       0
Bank Sta=250.031,274.658
XS Rating Curve= 0 ,0
Exp/Cntr(USF)=0,0
Exp/Cntr=0.3,0.1

Type RM Length L Ch R = 1 ,807     ,229.3,210.6,193
XS GIS Cut Line= 4
2021409.20019727194221.9400439762021241.37772295194310.904312334
2021072.13912831194329.7086006262020912.30267782194451.936474529
#Sta/Elev= 30
       01594.298   9.1871591.632   24.041586.404  38.8931580.031  53.7471572.078
  61.1731567.512   79.741554.338 116.8731525.748 140.8671510.074 157.7191502.004
 168.8591498.376 173.7221497.497 210.813 1494.75 237.221  1489.9 247.1241489.277
 257.0271488.006  266.931486.212 273.5321485.969 293.3381486.155 303.2411487.776
 309.8431488.966 319.746 1492.52 332.9511493.952 352.7571494.999 400.4431499.915
 437.4581501.499  500.651507.752 532.6081509.721 550.6751509.265  561.441511.056
#Mann= 3 ,-1 , 0
       0      .1       0 257.027    .045       0 303.241      .1       0
Bank Sta=257.027,303.241
XS Rating Curve= 0 ,0
Exp/Cntr(USF)=0,0
Exp/Cntr=0.5,0.3

Type RM Length L Ch R = 1 ,596     ,159.6,161,161.7
XS GIS Cut Line= 3
2021378.75125298 193904.572539332020964.54578221194286.161514044
2020922.87911558194329.564291835
#Sta/Elev= 30
       0 1542.86    14.2 1541.19    25.6  1540.7    42.8 1539.01    83.7 1533.99
   112.4 1529.87   130.2 1525.57   165.9 1524.82   174.8 1523.71   183.8 1521.36
   201.6 1513.64     215 1509.12   237.3 1500.64   241.6 1498.36   250.8 1489.42
   255.1 1488.05   275.2 1485.45   284.9 1484.04   301.9  1483.8   308.7 1484.06
   315.9 1485.42   325.1  1487.5   332.1 1488.29     353 1489.01   396.3 1491.67
   413.4 1493.36   430.2  1495.9   455.2 1498.06   541.6  1502.1   623.3 1508.02
#Mann= 8 ,-1 , 0
       0     .06       0      40     .04       0     240      .1       0
   275.2    .045       0   315.9     .04       0     390      .1       0
     440     .04       0     530      .1       0
#XS Ineff= 2 , 0
             195  1523.5     395          1523.5
Permanent Ineff=
       F       F
Bank Sta=275.2,315.9
XS Rating Curve= 0 ,0
Exp/Cntr(USF)=0,0
Exp/Cntr=0.5,0.3

Type RM Length L Ch R = 1 ,435     ,216.8,201.1,184.1
XS GIS Cut Line= 2
2021327.39300448 193751.439291822020816.97633776194234.078180715
#Sta/Elev= 30
       0 1527.51    30.3 1526.13    47.6 1525.26   110.8 1519.76     174 1508.61
   212.6 1501.46   236.9 1496.11   286.9 1483.64   298.5 1482.89   315.8 1483.68
   320.4 1484.36   341.3 1486.75   380.7 1487.09   403.6 1487.87   429.5 1492.35
   449.5 1493.66   460.9 1495.45   480.5 1498.12   510.7 1500.15   544.3 1502.75
   584.9  1504.4   601.2 1506.22     621 1507.98   656.7 1509.33   668.5 1512.13
   675.2 1511.54   679.7 1512.03   688.8 1515.81   696.4 1520.38   702.5 1522.59
#Mann= 11 ,-1 , 0
       0    .035       0    30.3     .04       0   110.8    .035       0
     174      .1       0   286.9    .045       0   315.8      .1       0
   320.4     .04       0   380.7      .1       0   460.9     .04       0
   510.7      .1       0   601.2     .04       0
#XS Ineff= 2 , 0
             266  1523.5     335          1523.5
Permanent Ineff=
       F       F
Bank Sta=286.9,315.8
XS Rating Curve= 0 ,0
Exp/Cntr(USF)=0,0
Exp/Cntr=0.5,0.3

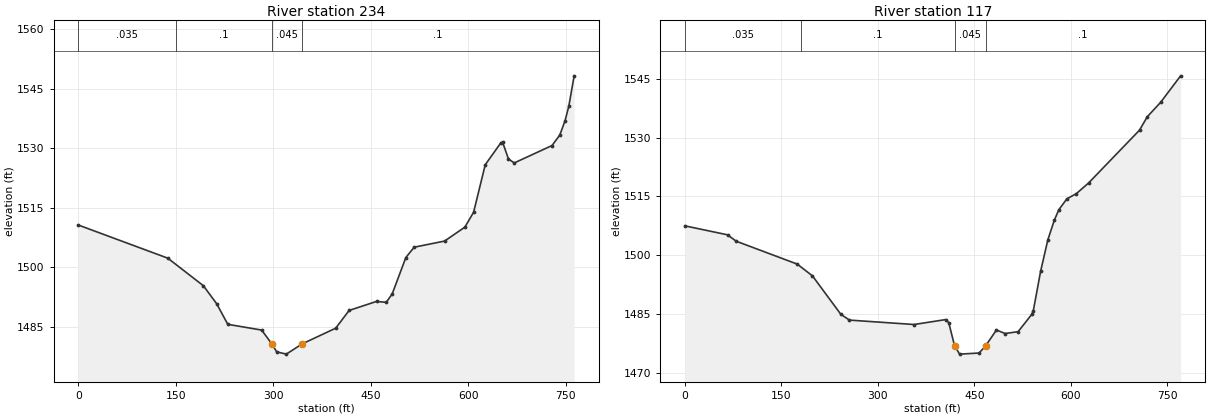
Type RM Length L Ch R = 1 ,234     ,119.3,116.5,113.2
XS GIS Cut Line= 4
2021195.27298371193712.1083634492020964.01447063193779.683168065
2020893.49838953193995.9324834312020677.24907417194195.728046541
#Sta/Elev= 30
       0 1510.67  137.641502.314 192.3291495.376 212.8371490.822 229.9271485.636
  282.031484.187 297.9171480.649 305.1831478.697 319.9891478.123 344.1451480.686
 395.9081484.661 416.6131489.136 458.7181491.409 473.691 1491.18 482.8761493.303
 503.8731502.479 516.7181505.083 563.4731506.625  594.741510.151 608.1411513.909
 626.0081525.869 650.1411531.424 652.8091531.507 661.7491527.313 670.6761526.327
 728.7441530.714 740.6881533.348  748.781536.944 754.6181540.659 762.8031548.285
#Mann= 4 ,-1 , 0
       0    .035       0     150      .1       0 297.917    .045       0
 344.145      .1       0
Bank Sta=297.917,344.145
XS Rating Curve= 0 ,0
Exp/Cntr(USF)=0,0
Exp/Cntr=0.3,0.1

Type RM Length L Ch R = 1 ,117     ,,,
XS GIS Cut Line= 4
2021140.57547169193627.2058420712020858.24034898193699.764942821
2020799.47694807193951.2722987362020663.14585795194125.211965443
#Sta/Elev= 30
       01507.479  66.3841505.188  79.934 1503.55 174.7821497.711 198.4941494.696
 242.531  1484.9 255.966 1483.41 356.4321482.284 405.6981483.548 410.3391482.748
 419.3531476.869 427.1851474.723 457.5081475.002 467.6151476.827 484.4611480.881
 497.9381479.988 518.1531480.454 539.5211484.906 541.7381485.763 553.1411495.873
 564.3721503.899 574.4151508.896 581.5121511.615 594.0171514.379 608.7731515.707
 627.5991518.403 706.9221531.916 719.0721535.356 739.6381538.999 770.791 1545.78
#Mann= 4 ,-1 , 0
       0    .035       0     180      .1       0 419.353    .045       0
 467.615      .1       0
Bank Sta=419.353,467.615
XS Rating Curve= 0 ,0
Exp/Cntr(USF)=0,0
Exp/Cntr=0.3,0.1
LCMann Table=0

Chan Stop Cuts=-1
Use User Specified Reach Order=0
Composite Channel Slope=5